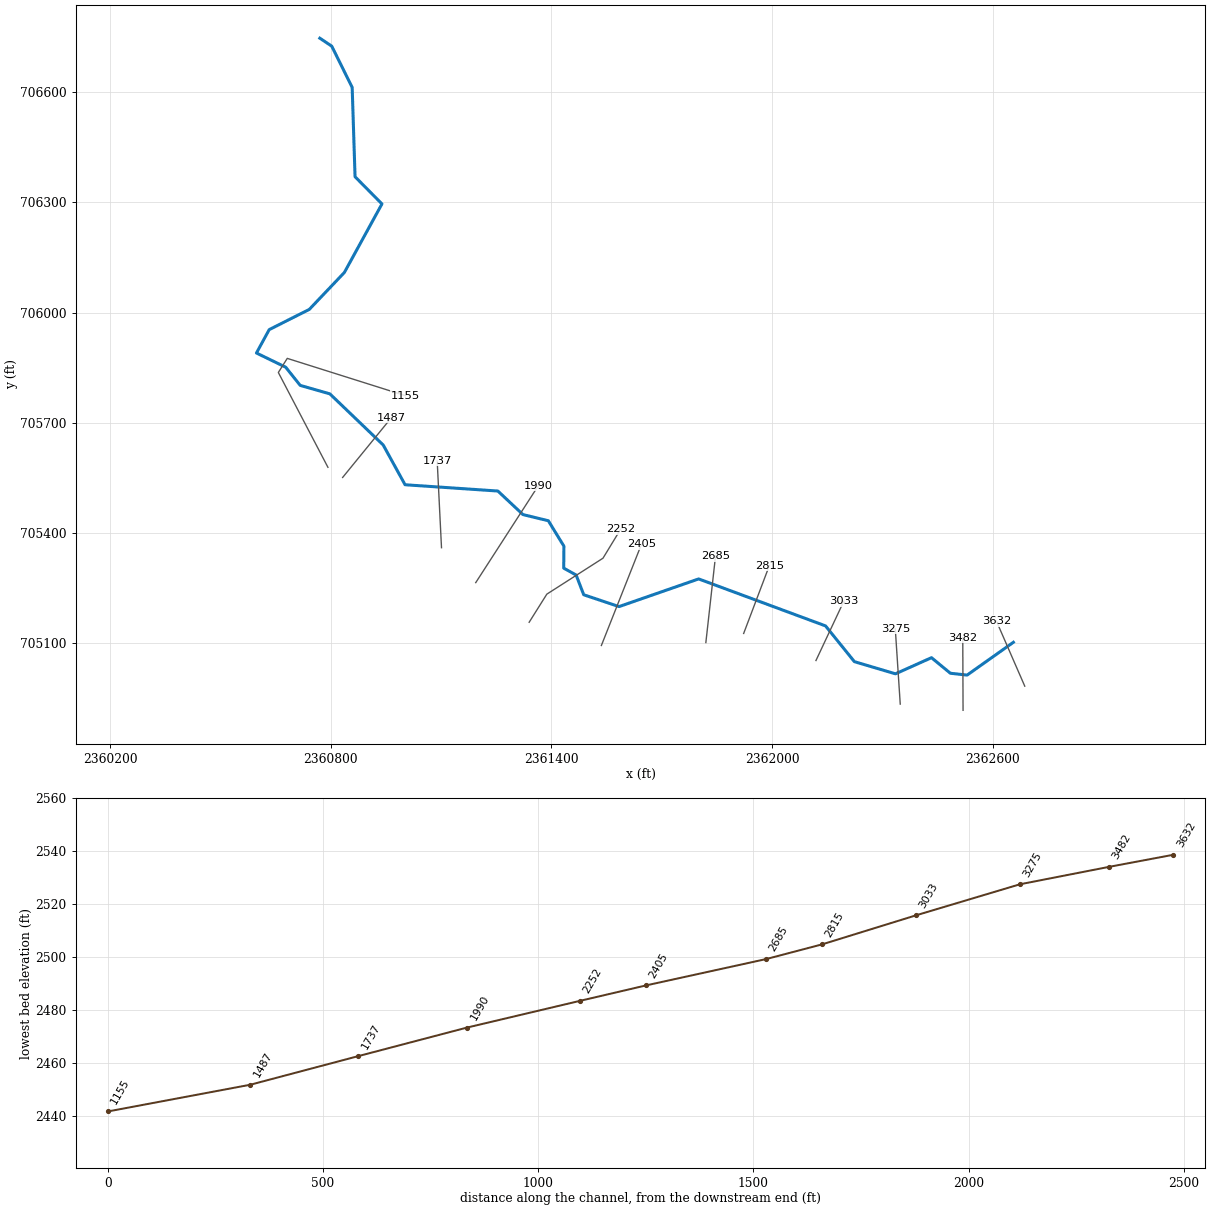
--- FIVELCKCK.prj (project) ---

Proj Title=FIVELCKCK
Current Plan=p01
Default Exp/Contr=0,0
English Units
Geom File=g01
Flow File=f01
Plan File=p01
BEGIN DESCRIPTION:
----------MODEL BY WOOD PLC 2022----------
AFH study
Randolph County, WV
HEC-RAS Version: RAS 6.2
Vertical Datum: NAVD88
Projection: NAD 1983 StatePlane West Virginia S FIPS 4702 (US Feet)
Terrain: 1-meter LIDAR (FEMA Region III 3DEP collected 2016-2018)
Land Use: 2019 NLCD
Hydrologic Method:
WV SIR2010-5033 regression equations
Additional Model Notes:
None
END DESCRIPTION:
DSS Export Rating Curves= 0
DSS Export Rating Curve Sorted= 0
DSS Export Volume Flow Curves= 0
DXF OffsetX= 0
DXF OffsetY= 0
DXF ScaleX= 0
DXF ScaleY= 0

--- FIVELCKCK.p01 (plan) ---

Plan Title=Floodplain
Program Version=6.20
Short Identifier=Floodplain
Geom File=g01
Flow File=f01
Subcritical Flow
K Sum by GR= 0
Std Step Tol= 0.01
Critical Tol= 0.01
Num of Std Step Trials= 20
Max Error Tol= 0.3
Flow Tol Ratio= 0.001
Split Flow NTrial= 30
Split Flow Tol= 0.02
Split Flow Ratio= 0.02
Log Output Level= 0
Friction Slope Method= 1
Unsteady Friction Slope Method= 2
Unsteady Bridges Friction Slope Method= 1
Parabolic Critical Depth
Global Vel Dist= 0 , 0 , 0
Global Log Level= 0
CheckData=True
Encroach Param=-1 ,0,0, 0
Mapping Interval=1HOUR
Computation Time Step Use Courant=        0
Computation Time Step Use Time Series=    0
Computation Time Step Count To Double=0
Computation Time Step Max Doubling=0
Computation Time Step Max Halving=0
Computation Time Step Residence Courant=0
Run HTab= 0
Run UNet= 0
Run Sediment= 0
Run PostProcess= 0
Run WQNet= 0
Run RASMapper=-1
UNET Theta= 0
UNET Theta Warmup= 0
UNET ZTol= 0
UNET ZSATol= 0
UNET MxIter= 0
UNET Max Iter WO Improvement= 0
UNET MaxInSteps= 0
UNET DtIC= 0
UNET DtMin= 0
UNET MaxCRTS= 0
UNET WFStab= 0
UNET SFStab= 0
UNET WFX= 1
UNET SFX= 1
UNET Gravity=32.174
UNET 1D Methodology=Finite Difference
UNET DSS MLevel= 1
UNET Pardiso=0
UNET DZMax Abort= 0
UNET Use Existing IB Tables= 0
UNET Froude Reduction=False
UNET Froude Limit= 0
UNET Froude Power= 0
UNET D1 Cores= 0
UNET WindReference=Eulerian
UNET WindDragFormulation=Hsu (1988)
UNET D2 Coriolis=0
UNET D2 Cores= 0
UNET D2 Theta= 1
UNET D2 Theta Warmup= 1
UNET D2 Z Tol= 0.01
UNET D2 Volume Tol= 0.01
UNET D2 Max Iterations= 20
UNET D2 Equation= 0
UNET D2 RampUpFraction=0.1
UNET D2 TimeSlices= 1
UNET D2 Turbulence Formulation=Non-Conservative (original)
UNET D2 Eddy Viscosity=0.3
UNET D2 Transverse Eddy Viscosity=0.1
UNET D2 Smagorinsky Mixing=0
UNET D2 BCVolumeCheck=0
UNET D2 Cores=0
UNET D2 SolverType=PARDISO (Direct)
UNET D2 Minimum Iterations= 2147483647
UNET D2 Maximum Iterations= 2147483647
UNET D2 Restart Number= 10
UNET D2 Relaxation Coeff=1.3
UNET D2 SOR Precondition Iterations= 10
UNET D2 ILUT Maximum Fill= 8
UNET D2 ILUT Tolerance=1E-08
UNET D1D2 MaxIter= 0
UNET D1D2 ZTol=0.01
UNET D1D2 QTol=0.1
UNET D1D2 MinQTol=1
Write IC File= 0
Write IC File at Fixed DateTime=0
Write IC File at Sim End=0
Echo Input=False
Echo Parameters=False
Echo Output=False
Write Detailed= 0
HDF Write Warmup=0
HDF Write Time Slices=0
HDF Flush=0
HDF Compression= 1
HDF Chunk Size= 1
HDF Spatial Parts= 1
HDF Use Max Rows=0
HDF Fixed Rows= 1
Calibration Method= 0
Calibration Iterations= 20
Calibration Max Change=0.05
Calibration Tolerance=0.2
Calibration Maximum=1.5
Calibration Minimum=0.5
Calibration Optimization Method= 1
WQ AD Non Conservative
WQ ULTIMATE=-1
WQ Max Comp Step=1HOUR
WQ Output Interval=15MIN
WQ Output Selected Increments= 0
WQ Output face flow=0
WQ Output face velocity=0
WQ Output face area=0
WQ Output face dispersion=0
WQ Output cell volume=0
WQ Output cell surface area=0
WQ Output cell continuity=0
WQ Output cumulative cell continuity=0
WQ Output face conc=0
WQ Output face dconc_dx=0
WQ Output face courant=0
WQ Output face peclet=0
WQ Output face adv mass=0
WQ Output face disp mass=0
WQ Output cell mass=0
WQ Output cell source sink temp=0
WQ Output nsm pathways=0
WQ Output nsm derived pathways=0
WQ Create Restart=0
WQ Fixed Restart=0
WQ System Summary=0
WQ Write To DSS=0
Sorting and Armoring Iterations= 10
XS Update Threshold= 0.02
Bed Roughness Predictor= 0
Hydraulics Update Threshold= 0.02
Energy Slope Method= 1
Volume Change Method= 1
Sediment Retention Method= 0
Sediment TS Multiplier= 1
Warm Up Method= 0
XS Weighting Method= 0
Number of US Weighted Cross Sections= 1
Number of DS Weighted Cross Sections= 1
Upstream XS Weight=0
Main XS Weight=1
Downstream XS Weight=0
Number of DS XS's Weighted with US Boundary= 1
Upstream Boundary Weight= 1
Weight of XSs Associated with US Boundary= 0
Number of US XS's Weighted with DS Boundary= 1
Downstream Boundary Weight= 0.5
Weight of XSs Associated with DS Boundary= 0.5
Percentile Method= 0
Sediment Output Level= 3
Mass or Volume Output= 0
Output Increment Type= 1
Profile and TS Output Increment= 1
Transport Output Increment 1
XS Output Flag= 0
XS Output Increment= 10
Read HDF5 Sediment Hotstart= 0
Sediment Hotstart Type= 0
Write Gradation File= 0
Read Gradation Hotstart= 0
Write HDF5 File= 1
Write Binary Output= 1
Write DSS Sediment File= 0
DSS Sediment Output Type= 1
SV Curve= 0
Specific Gage Flag= 0
Subcell Erosion Methods= 0
Subcell Deposition Methods= 0
Advection Scheme= 1
Matrix Solver= 0
Implicit Weighting Factor= 1
Maximum Outer Loop Convergence Iterations= 5
Convergence Maximum Absolute= 0.001
Convergence RMSE= 0.0001
Grain Fractions Max Abs Error= 0.001
Max Subgrid Regions= 1
Max Subgrid Length Scale= 3.402823E+38
Initial Layer Thickness= 3.402823E+38
Min Layer Thickness= 3.402823E+38
Max Layer Thickness= 3.402823E+38
Number of Layers= 5

--- FIVELCKCK.f01 (steady flow) ---

Flow Title=Flow
Program Version=6.20
Number of Profiles= 1
Profile Names=P100yr
River Rch & RM=FIVELCKCK,Main,3632
     362
Boundary for River Rch & Prof#=FIVELCKCK,Main            , 1
Up Type= 0
Dn Type= 3
Dn Slope=0.02961
DSS Import GetInterval= 0
DSS Import GetPeak= 0
DSS Import FillOption= 0

--- FIVELCKCK.g01 (geometry) ---

Geom Title=Geometry
Program Version=6.20

River Reach=FIVELCKCK       ,Main
Reach XY= 30
2362656.34562637705102.9539381272362530.51000002      705013.816
2362485.01299998705018.7569999992362433.62400001705061.118000016
2362335.60211027705017.2071764622362223.90200001705050.354000017
2362145.42900002 705147.576000022361800.29099999705275.354000002
2361583.73800001705200.0760000052361487.70200001705232.247999996
2361467.05609405705285.9019889682361433.31652923705304.681293905
2361433.73900002705364.4780000152361391.43700004705433.574000001
     2361322.367      705450.375     2361254.145705514.415999994
     2361001.714 705531.51700002     2360942.252705639.590000004
2360797.14400001705778.7479999962360716.47188666705801.784090847
2360677.04700002705851.1930000192360597.47100002705889.828000009
2360632.15700001      705953.4122360741.11900002706008.341000021
2360836.58400001706108.7940000152360938.84100004 706295.32100001
2360865.66400005706369.280000016     2360857.846706612.222000003
2360802.33538712706724.360003241      2360769.84      706746.124

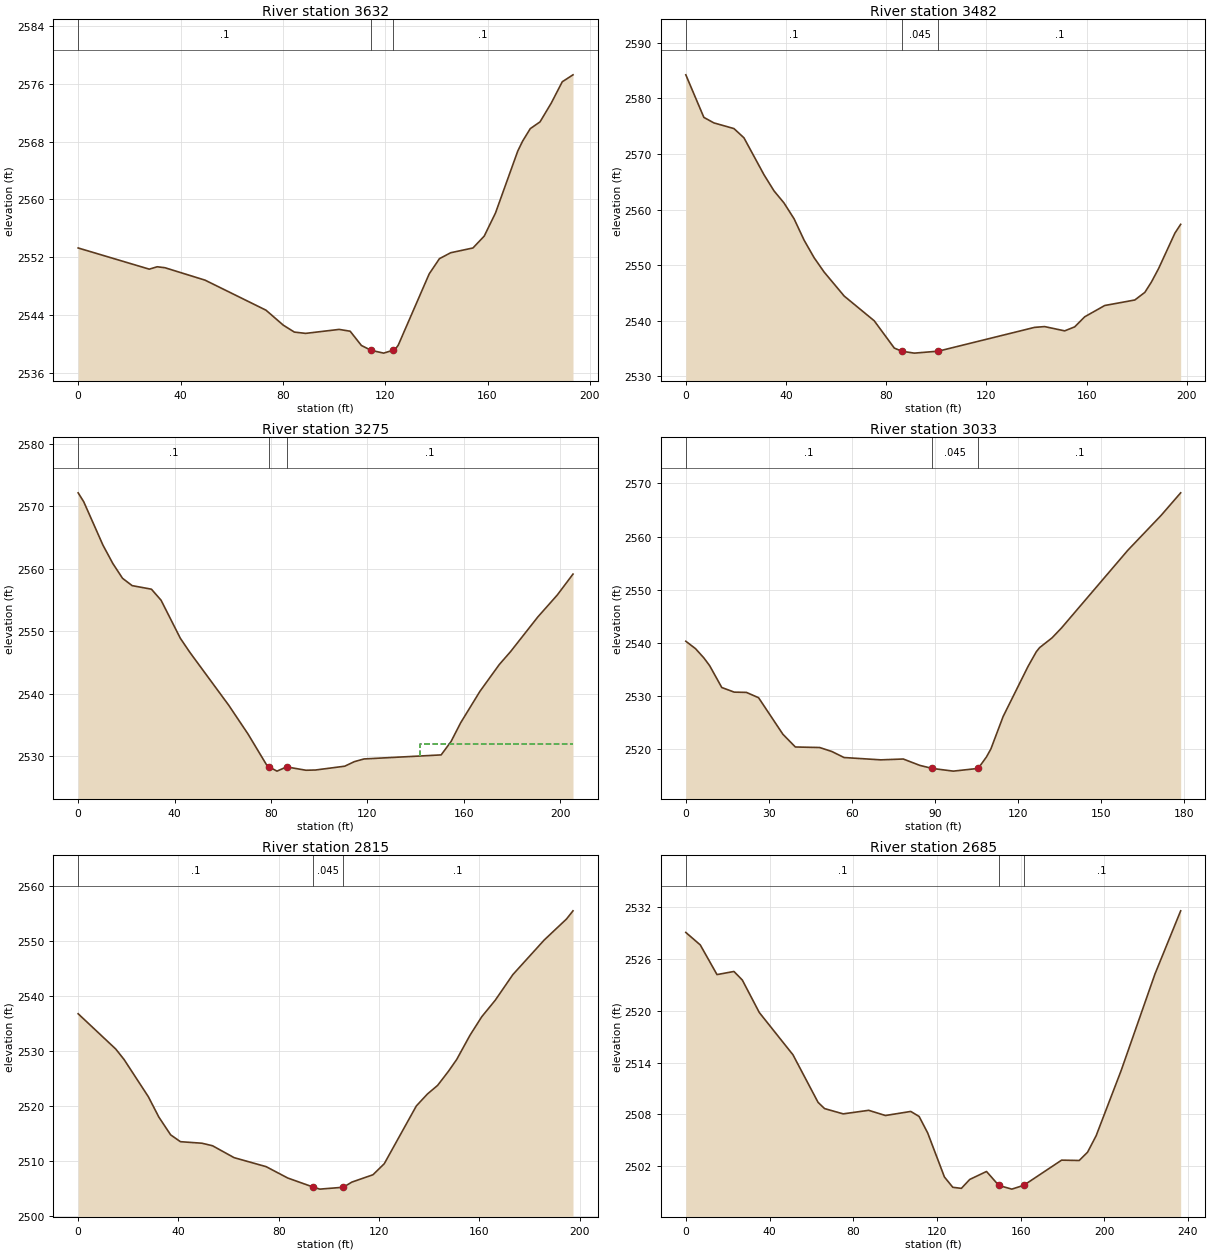
Type RM Length L Ch R = 1 ,3632    ,153.4,149.3,145.9
XS GIS Cut Line= 2
 2362687.3126289704983.6887955622362610.06655121705160.991873215
#Sta/Elev= 30
       0 2553.29    27.8 2550.36    30.9 2550.69    33.9 2550.56    49.6 2548.84
    73.4 2544.69    80.2 2542.61    84.5 2541.66    88.9 2541.48     102 2542.03
   106.3 2541.78   110.7 2539.81   114.42539.148   119.4 2538.75   122.9 2539.13
   123.8 2539.21   125.1 2539.85   137.2 2549.71   141.2 2551.81   145.6 2552.63
   154.3 2553.29   158.7 2554.93   163.1 2558.12   171.8 2566.68   173.7 2568.06
   176.7 2569.79   180.5 2570.72   184.9 2573.32   189.2 2576.27   193.4 2577.23
#Mann= 3 ,-1,0
       0      .1       0   114.4    .045       0   122.9      .1       0
Bank Sta=114.4,122.9
XS Rating Curve= 0 ,0
Exp/Cntr(USF)=0,0
Exp/Cntr=0.3,0.1

Type RM Length L Ch R = 1 ,3482    ,206.9,207.4,206.8
XS GIS Cut Line= 2
2362519.49667238704917.9484302182362518.70650312705115.490745267
#Sta/Elev= 30
       0 2584.21     7.2 2576.56    11.2 2575.57    19.2 2574.55    23.2 2572.89
    31.2 2566.25    35.2 2563.35    39.2 2561.17    43.2 2558.34    47.2  2554.5
    51.2 2551.34    55.2 2548.76    63.2 2544.45    75.2    2540    83.2  2535.1
    86.2 2534.53    91.2 2534.19   100.82534.544   139.2 2538.82   143.2 2538.96
   151.2 2538.19   155.2 2538.91   159.2 2540.72   167.2 2542.75   179.2 2543.74
   183.2 2545.11   185.8 2546.95   188.7  2549.4   195.2 2555.76   197.5 2557.34
#Mann= 3 ,-1,0
       0      .1       0    86.2    .045       0   100.8      .1       0
Bank Sta=86.2,100.8
XS Rating Curve= 0 ,0
Exp/Cntr(USF)=0,0
Exp/Cntr=0.3,0.1

Type RM Length L Ch R = 1 ,3275    ,242.6,241.6,239.9
XS GIS Cut Line= 2
2362348.64375923704934.8568895962362335.13186488705139.668761839
#Sta/Elev= 30
       0 2572.19     2.3 2570.77    10.3  2563.8    14.4 2560.86    18.4  2558.5
    22.4 2557.32    30.4 2556.75    34.4 2554.98    42.4 2548.88    46.4  2546.6
    62.5 2538.14    70.5 2533.53    78.5 2528.39    79.2 2528.27    82.5  2527.6
    86.5 2528.28    94.5 2527.74    98.5 2527.78   110.6 2528.39   114.6 2529.12
   118.6 2529.55   150.6  2530.2   154.7 2532.34   158.7 2535.35   166.7 2540.39
   174.7 2544.67   179.4 2546.75   190.7  2552.3   198.8 2555.83   205.3 2559.17
#Mann= 3 ,-1,0
       0      .1       0    79.2    .045       0    86.5      .1       0
#XS Ineff= 2 , 0
                          141.66         2532.02
Permanent Ineff=
       F       F
Bank Sta=79.2,86.5
XS Rating Curve= 0 ,0
Exp/Cntr(USF)=0,0
Exp/Cntr=0.3,0.1

Type RM Length L Ch R = 1 ,3033    ,217.7,218.1,218.8
XS GIS Cut Line= 2
2362119.36383102705053.3788410942362195.45420423705215.314763554
#Sta/Elev= 30
       0  2540.3     3.5 2538.91     6.5 2537.18     8.6 2535.72      13  2531.6
    17.5 2530.73    21.9 2530.68    26.3 2529.68    35.1  2522.8    39.6 2520.41
    48.4 2520.31    52.8 2519.56    57.2 2518.43    70.5 2517.99    78.6 2518.15
    84.6 2516.95   89.17 2516.37    96.7 2515.87   105.7 2516.38   108.7 2518.55
   110.3 2520.06   114.7 2526.13   123.7 2535.55   126.7 2538.32   127.9  2539.1
   132.4 2540.94   135.8 2542.79   159.8 2557.42   171.8 2563.96   178.9 2568.22
#Mann= 3 ,-1,0
       0      .1       0   89.17    .045       0   105.7      .1       0
Bank Sta=89.17,105.7
XS Rating Curve= 0 ,0
Exp/Cntr(USF)=0,0
Exp/Cntr=0.3,0.1

Type RM Length L Ch R = 1 ,2815    ,127.5,129.7,130.5
XS GIS Cut Line= 2
2361922.72382911705127.0199584482361992.60844461705311.639254128
#Sta/Elev= 30
       0 2536.77      15 2530.36    18.3 2528.47      28  2521.7    32.2 2517.99
    36.9 2514.77    40.8 2513.53    49.4 2513.25    53.6 2512.79    62.2 2510.63
      75 2508.99    83.6 2506.93   93.84 2505.27    96.4 2504.91  105.74 2505.25
   109.2 2506.19   117.6 2507.52   122.1 2509.52   134.9 2520.02   139.3 2522.18
   143.4 2523.76   147.7 2526.31     151 2528.46   156.3 2532.86     161 2536.23
   166.4 2539.24   173.4 2543.88   185.9 2550.16   194.8 2553.98   197.4 2555.47
#Mann= 3 ,-1,0
       0      .1       0   93.84    .045       0  105.74      .1       0
Bank Sta=93.84,105.74
XS Rating Curve= 0 ,0
Exp/Cntr=0.3,0.1

Type RM Length L Ch R = 1 ,2685    ,281,280,278.7
XS GIS Cut Line= 2
2361819.88624223705102.3386106142361846.16421174705337.377345962
#Sta/Elev= 30
       0 2529.04     6.9  2527.6    14.9 2524.17      23 2524.53      27 2523.54
    35.1 2519.79    51.2  2514.9    63.2  2509.4    66.3 2508.68    75.2 2508.07
    87.4 2508.48    95.4 2507.88   107.5 2508.35   111.5 2507.77   115.6 2505.86
   123.6 2500.77   127.6 2499.58   131.7 2499.46   135.7 2500.49   143.7 2501.41
  149.57  2499.8   155.8 2499.37   161.5 2499.81   179.6 2502.72     188 2502.68
     192 2503.64   196.1 2505.54   208.1 2513.11   224.2 2524.23   236.5 2531.54
#Mann= 3 ,-1,0
       0      .1       0  149.57    .045       0   161.5      .1       0
Bank Sta=149.57,161.5
XS Rating Curve= 0 ,0
Exp/Cntr(USF)=0,0
Exp/Cntr=0.3,0.1

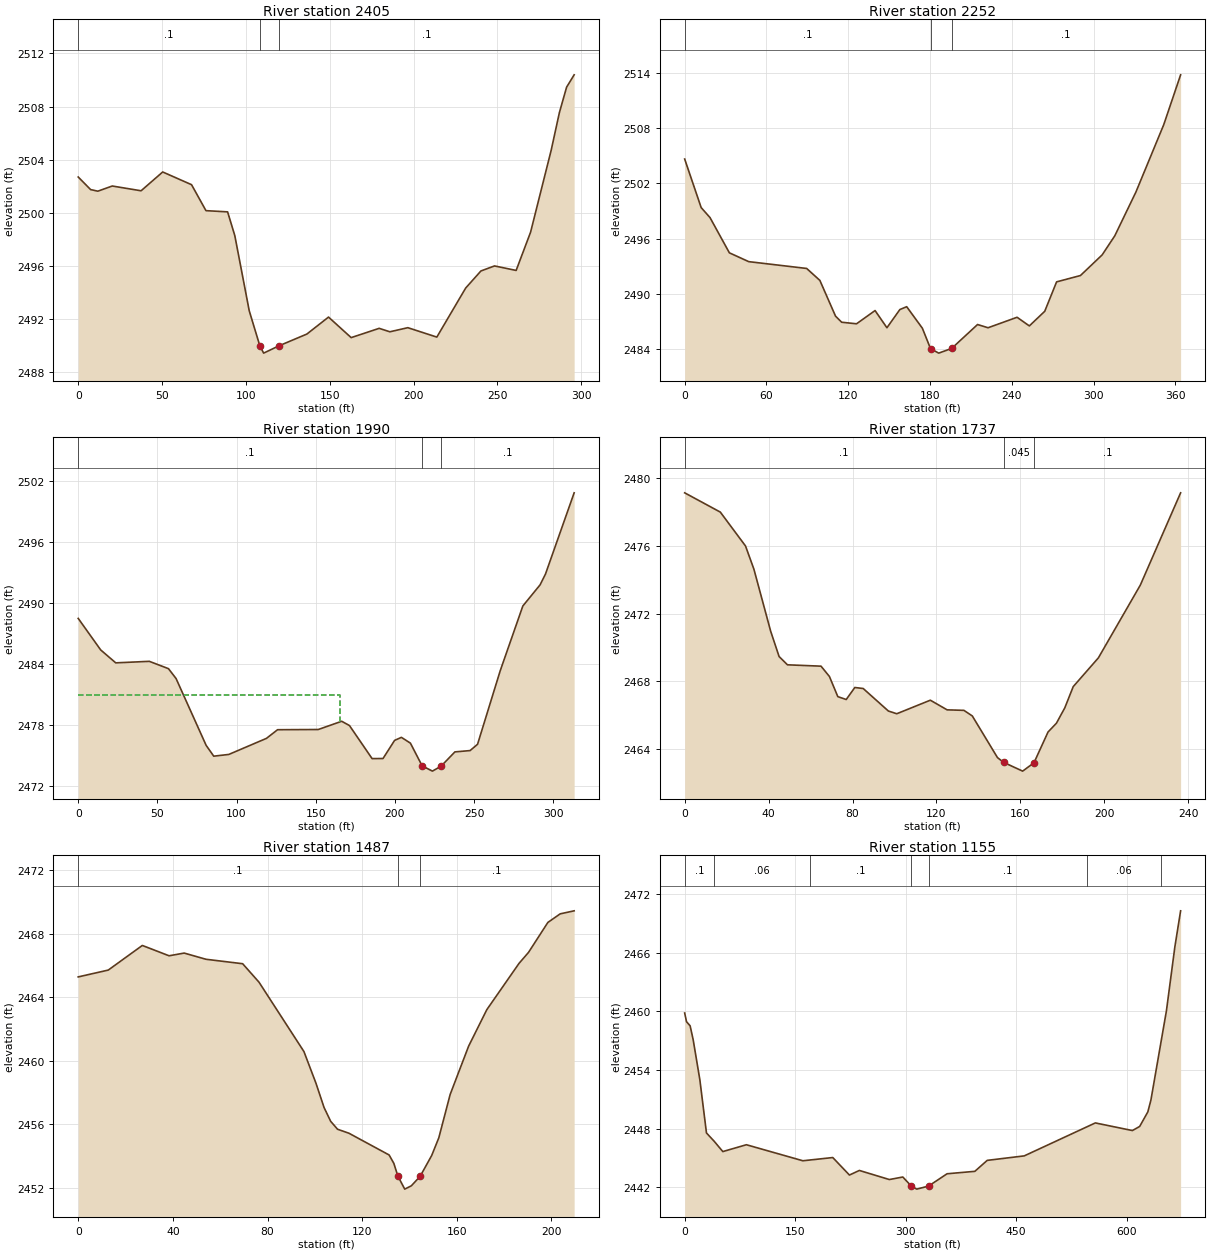
Type RM Length L Ch R = 1 ,2405    ,156.6,153.7,148.1
XS GIS Cut Line= 2
2361535.71325835705094.3379464592361644.66005959705369.393204016
#Sta/Elev= 30
       0 2502.68     7.4 2501.73    11.7 2501.61    20.3    2502    37.5 2501.64
    50.4 2503.06    67.6  2502.1    76.2 2500.14    89.1 2500.05    93.4 2498.26
     102 2492.59  108.38 2489.92   110.6 2489.39   119.52489.928   136.4 2490.83
   149.3 2492.11   162.8 2490.56   179.5 2491.26   185.9    2491   196.6 2491.31
   213.9  2490.6   231.1  2494.3   240.2 2495.59   248.3 2495.97   261.2 2495.63
   269.8 2498.51   282.1  2504.7     287 2507.54   291.3 2509.46   295.8 2510.39
#Mann= 3 ,-1,0
       0      .1       0  108.38    .045       0   119.5      .1       0
Bank Sta=108.38,119.5
XS Rating Curve= 0 ,0
Exp/Cntr(USF)=0,0
Exp/Cntr=0.3,0.1

Type RM Length L Ch R = 1 ,2252    ,256.8,261.9,262.1
XS GIS Cut Line= 4
2361339.21240871705157.4027239762361387.33334597705233.952516654
2361540.05660437 705331.695402032361587.97429236705410.373756006
#Sta/Elev= 30
       0 2504.66    12.1 2499.38    18.6 2498.29    32.8 2494.46      47  2493.5
    89.5 2492.76    99.2 2491.46   110.7 2487.57   115.2 2486.91   126.1 2486.74
   139.7 2488.18   148.4 2486.31   157.9 2488.29   162.9  2488.6   174.4 2486.26
  180.39 2484.04   186.4 2483.55   195.9 2484.06   214.9 2486.66   222.6 2486.31
   243.9 2487.45   252.9 2486.51   264.2  2488.1   272.9  2491.3   290.4 2491.99
   306.3 2494.23   315.6 2496.31   331.1 2501.07   351.5 2508.39   363.9 2513.82
#Mann= 3 ,-1,0
       0      .1       0  180.39    .045       0   195.9      .1       0
Bank Sta=180.39,195.9
XS Rating Curve= 0 ,0
Exp/Cntr(USF)=0,0
Exp/Cntr=0.3,0.1

Type RM Length L Ch R = 1 ,1990    ,247,252.6,255.3
XS GIS Cut Line= 2
2361193.95983415 705265.28694056 2361363.8462251705528.413304205
#Sta/Elev= 30
       0 2488.49    14.2 2485.39    23.7 2484.12    44.9 2484.27      57 2483.55
    61.8 2482.58    80.8 2476.01    85.6 2474.95    95.1 2475.12   118.9  2476.7
   125.9 2477.55   151.6 2477.57   166.4 2478.38   171.3 2477.96   185.6 2474.71
   192.5 2474.72   199.8  2476.5   204.1  2476.8   209.8 2476.23   217.22473.997
   223.7 2473.48   229.22473.972   237.9 2475.37   247.5  2475.5   252.2 2476.12
   266.5 2483.34   280.8 2489.71   291.7 2491.79   295.1 2492.85   313.2 2500.83
#Mann= 3 ,-1,0
       0      .1       0   217.2    .045       0   229.2      .1       0
#XS Ineff= 2 , 0
          165.61 2480.97
Permanent Ineff=
       F       F
Bank Sta=217.2,229.2
XS Rating Curve= 0 ,0
Exp/Cntr(USF)=0,0
Exp/Cntr=0.3,0.1

Type RM Length L Ch R = 1 ,1737    ,256.9,250.6,245.9
XS GIS Cut Line= 2
2361100.82600268705360.227972958 2361089.0924822705596.368068063
#Sta/Elev= 30
       0 2479.14      17    2478      29    2476      33 2474.63      41 2470.96
      45 2469.47      49 2468.98      65  2468.9      69 2468.29      73  2467.1
      77 2466.93    81.1 2467.64    85.1 2467.58    97.1 2466.25   101.1 2466.09
   117.1 2466.89   125.1 2466.32   133.1 2466.29   137.1 2465.96   149.1  2463.5
     152 2463.22   161.1  2462.7   166.52463.192   173.2 2465.01   177.2 2465.53
   181.2 2466.44   185.2 2467.69   197.2 2469.39   217.2 2473.69   236.4 2479.14
#Mann= 3 ,-1,0
       0      .1       0     152    .045       0   166.5      .1       0
Bank Sta=152,166.5
XS Rating Curve= 0 ,0
Exp/Cntr=0.3,0.1

Type RM Length L Ch R = 1 ,1487    ,329.8,331.2,331
XS GIS Cut Line= 2
2360831.88125136705551.3256350572360964.38007787 705713.79724034
#Sta/Elev= 30
       0 2465.27    12.7  2465.7    27.1 2467.25    38.4  2466.6    44.8 2466.77
      54 2466.38    69.5  2466.1    76.4 2464.94    95.4 2460.57   100.5 2458.57
   103.9 2457.05   106.7 2456.18   109.6 2455.68   114.4 2455.43   131.4 2454.06
   133.4 2453.53   135.1 2452.73     138 2451.91   140.8 2452.12  144.53 2452.72
   149.4 2454.03   152.4 2455.14   157.2 2457.87     165 2460.91   172.7 2463.21
   186.3 2466.12   190.3 2466.81   198.5  2468.7   203.7 2469.24   209.6 2469.43
#Mann= 3 ,-1,0
       0      .1       0   135.1    .045       0  144.53      .1       0
Bank Sta=135.1,144.53
XS Rating Curve= 0 ,0
Exp/Cntr(USF)=0,0
Exp/Cntr=0.3,0.1

Type RM Length L Ch R = 1 ,1155    ,,,
XS GIS Cut Line= 4
 2360791.8919132705578.9636365252360656.99006487705836.852943858
2360681.28736051 705875.228334792361002.57860744705773.819452687
#Sta/Elev= 30
       0 2459.82     2.5 2458.93     7.4 2458.51    11.5  2457.1    20.6    2453
    29.6 2447.55      40 2446.71    51.8 2445.65    83.8 2446.35   160.5 2444.71
   201.1 2445.04   223.7 2443.25   237.2 2443.72   277.9 2442.79   296.2 2443.05
   307.6 2442.13   315.1 2441.81  331.08 2442.12   356.3 2443.38     394 2443.63
   410.8 2444.75   461.1 2445.21   557.6 2448.58   607.9  2447.8   617.8 2448.22
   628.9 2449.71   633.1 2450.93   654.1 2460.03   665.6 2466.59   673.4 2470.27
#Mann= 7 ,-1,0
       0      .1       0      40     .06       0     170      .1       0
   307.6    .045       0  331.08      .1       0  546.46     .06       0
  646.46      .1       0
Bank Sta=307.6,331.08
XS Rating Curve= 0 ,0
Exp/Cntr(USF)=0,0
Exp/Cntr=0.3,0.1
LCMann Table=0

Chan Stop Cuts=-1
Use User Specified Reach Order=0
Composite Channel Slope=5